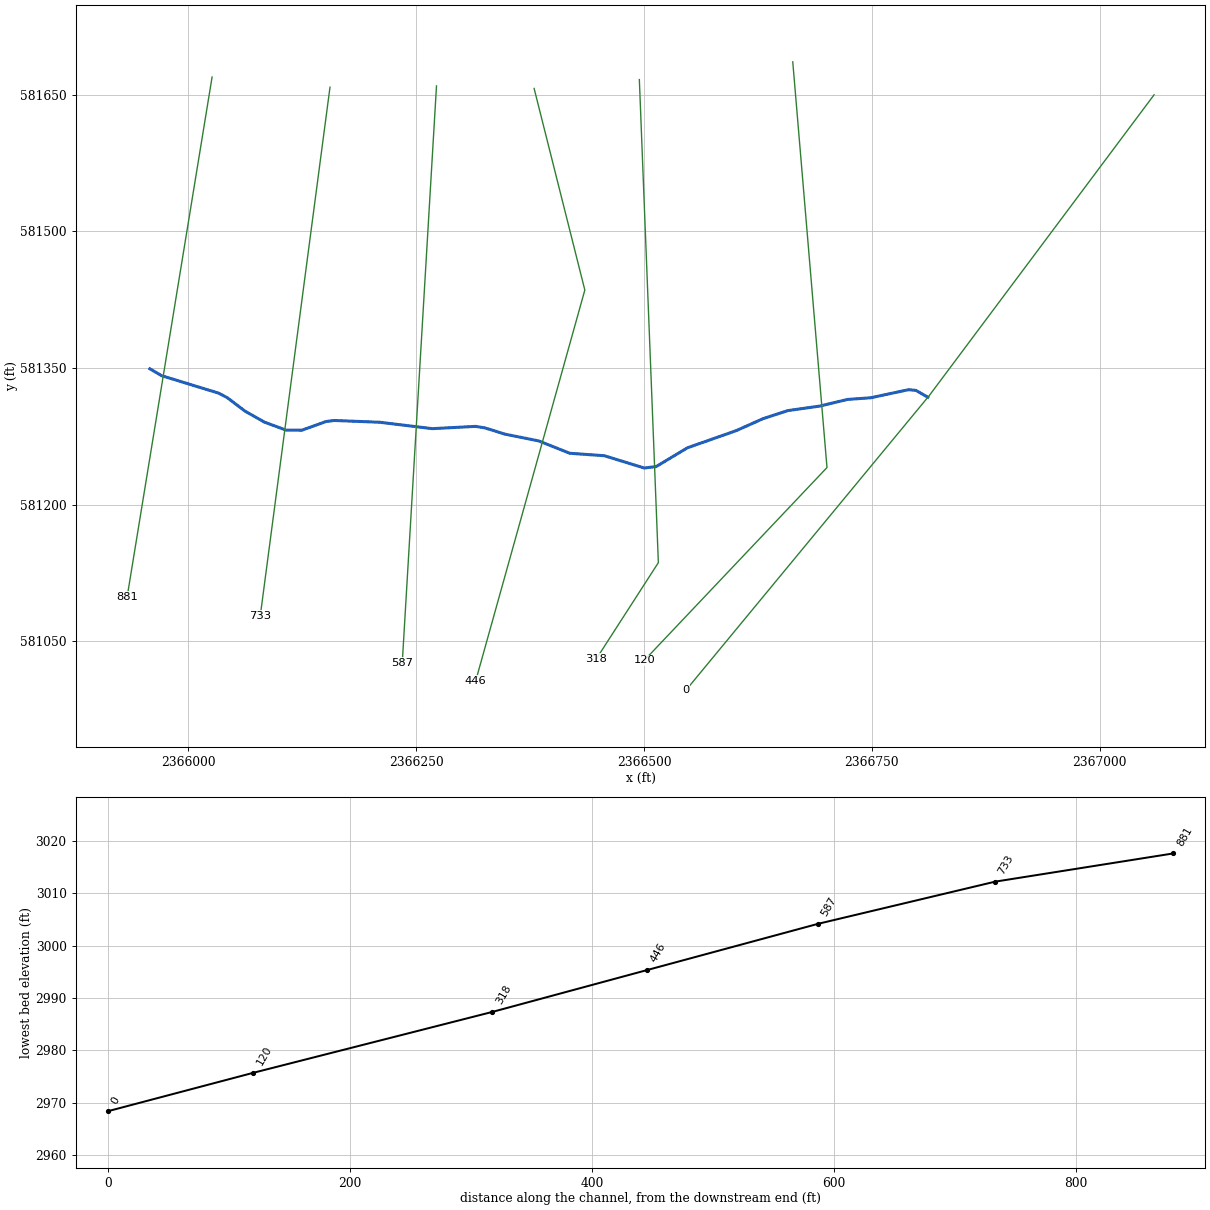
--- VANCERN_T1.prj (project) ---

Proj Title=VANCERN_T1
Current Plan=p01
Default Exp/Contr=0.3,0.1
English Units
Geom File=g01
Flow File=f01
Plan File=p01
Y Axis Title=Elevation
X Axis Title(PF)=Main Channel Distance
X Axis Title(XS)=Station
BEGIN DESCRIPTION:
Stream Name: Vance Run Tributary 1
Flood Zone: Approximate
Pendleton County, West Virginia
HEC-RAS Version: 5.0.7
Hydrology Method:
Regression equation
END DESCRIPTION:
DSS Export Rating Curves= 0
DSS Export Rating Curve Sorted= 0
DSS Export Volume Flow Curves= 0
DXF OffsetX= 0
DXF OffsetY= 0
DXF ScaleX= 1
DXF ScaleY= 10

--- VANCERN_T1.p01 (plan) ---

Plan Title=Floodplain
Program Version=5.07
Short Identifier=Floodplain
Geom File=g01
Flow File=f01
Subcritical Flow
K Sum by GR= 0
Std Step Tol= 0.01
Critical Tol= 0.01
Num of Std Step Trials= 20
Max Error Tol= 0.3
Flow Tol Ratio= 0.001
Split Flow NTrial= 30
Split Flow Tol= 0.02
Split Flow Ratio= 0.02
Log Output Level= 0
Friction Slope Method= 1
Unsteady Friction Slope Method= 2
Unsteady Bridges Friction Slope Method= 1
Parabolic Critical Depth
Global Vel Dist= 0 , 0 , 0
Global Log Level= 0
CheckData=True
Encroach Param=-1 ,0,0, 0
Computation Interval=1MIN
Output Interval=1HOUR
Instantaneous Interval=1HOUR
Mapping Interval=1HOUR
Computation Time Step Use Courant=        0
Computation Time Step Use Time Series=    0
Computation Time Step Count To Double=0
Computation Time Step Max Doubling=0
Computation Time Step Max Halving=0
Computation Time Step Residence Courant=0
Run HTab= 0
Run UNet= 0
Run Sediment= 0
Run PostProcess= 0
Run WQNet= 0
Run RASMapper= 0
UNET Theta= 1
UNET Theta Warmup= 1
UNET ZTol= 0.02
UNET ZSATol= 0.02
UNET MxIter= 20
UNET Max Iter WO Improvement= 0
UNET MaxInSteps= 0
UNET DtIC= 0
UNET DtMin= 0
UNET MaxCRTS= 20
UNET WFStab= 2
UNET SFStab= 1
UNET WFX= 1
UNET SFX= 1
UNET 1D Methodology=Finite Difference
UNET DSS MLevel= 4
UNET Pardiso=0
UNET DZMax Abort= 100
UNET Use Existing IB Tables=-1
UNET Froude Reduction=False
UNET Froude Limit= 0.8
UNET Froude Power= 4
UNET D1 Cores= 0
UNET D2 Coriolis=0
UNET D2 Cores= 0
UNET D2 Theta= 1
UNET D2 Theta Warmup= 1
UNET D2 Z Tol= 0.01
UNET D2 Volume Tol= 0.01
UNET D2 Max Iterations= 20
UNET D2 Equation= 0
UNET D2 RampUpFraction=0.1
UNET D2 TimeSlices= 1
UNET D2 BCVolumeCheck=0
UNET D1D2 MaxIter= 0
UNET D1D2 ZTol=0.01
UNET D1D2 QTol=0.1
UNET D1D2 MinQTol=1
Write IC File= 0
Write IC File at Fixed DateTime=0
Write IC File at Sim End=0
Echo Input=False
Echo Parameters=False
Echo Output=False
Write Detailed= 0
HDF Write Warmup=0
HDF Write Time Slices=0
HDF Flush=0
HDF Face Node Velocities=0
HDF Compression= 1
HDF Chunk Size= 1
HDF Spatial Parts= 1
HDF Use Max Rows=0
HDF Fixed Rows= 1
Calibration Method= 0
Calibration Iterations= 20
Calibration Max Change=0.05
Calibration Tolerance=0.2
Calibration Maximum=1.5
Calibration Minimum=0.5
Calibration Optimization Method= 1
WQ AD Non Conservative
WQ ULTIMATE=-1
WQ Max Comp Step=1HOUR
WQ Output Interval=15MIN
WQ Output Selected Increments= 0
WQ Output face flow=0
WQ Output face velocity=0
WQ Output face area=0
WQ Output face dispersion=0
WQ Output cell volume=0
WQ Output cell surface area=0
WQ Output cell continuity=0
WQ Output cumulative cell continuity=0
WQ Output face conc=0
WQ Output face dconc_dx=0
WQ Output face courant=0
WQ Output face peclet=0
WQ Output face adv mass=0
WQ Output face disp mass=0
WQ Output cell mass=0
WQ Output cell source sink temp=0
WQ Output nsm pathways=0
WQ Output nsm derived pathways=0
WQ Output MaxMinRange=-1
WQ Daily Max Min Mean=-1
WQ Daily Range=0
WQ Daily Time=0
WQ Create Restart=0
WQ Fixed Restart=0
WQ System Summary=0
WQ Write To DSS=0
WQ Use Fixed Temperature=0
Sorting and Armoring Iterations= 10
XS Update Threshold= 0.02
Bed Roughness Predictor= 0
Hydraulics Update Threshold= 0.02
Energy Slope Method= 1
Volume Change Method= 1
Sediment Retention Method= 0
XS Weighting Method= 0
Number of US Weighted Cross Sections= 1
Number of DS Weighted Cross Sections= 1
Upstream XS Weight=0
Main XS Weight=1
Downstream XS Weight=0
Number of DS XS's Weighted with US Boundary= 1
Upstream Boundary Weight= 1
Weight of XSs Associated with US Boundary= 0
Number of US XS's Weighted with DS Boundary= 1
Downstream Boundary Weight= 0.5
Weight of XSs Associated with DS Boundary= 0.5
Percentile Method= 0
Sediment Output Level= 3
Mass or Volume Output= 0
Output Increment Type= 1
Profile and TS Output Increment= 1
XS Output Flag= 0
XS Output Increment= 10
Write Gradation File= 0
Read Gradation Hotstart= 0
Write HDF5 File= 1
Write Binary Output= 1
Write DSS Sediment File= 0
SV Curve= 0
Specific Gage Flag= 0

--- VANCERN_T1.f01 (steady flow) ---

Flow Title=Flows
Program Version=5.07
Number of Profiles= 6
Profile Names=P100yr,P10yr,P25yr,P50yr,P500yr,P101yr
River Rch & RM=VANCERN_T1,Main            ,881
     575     269     380     475     843     700
Boundary for River Rch & Prof#=VANCERN_T1,Main            , 1
Up Type= 0
Dn Type= 1
Dn Known WS=2971.87
Boundary for River Rch & Prof#=VANCERN_T1,Main            , 2
Up Type= 0
Dn Type= 1
Dn Known WS=2970.66
Boundary for River Rch & Prof#=VANCERN_T1,Main            , 3
Up Type= 0
Dn Type= 1
Dn Known WS=2971.14
Boundary for River Rch & Prof#=VANCERN_T1,Main            , 4
Up Type= 0
Dn Type= 1
Dn Known WS=2971.52
Boundary for River Rch & Prof#=VANCERN_T1,Main            , 5
Up Type= 0
Dn Type= 1
Dn Known WS=2972.72
Boundary for River Rch & Prof#=VANCERN_T1,Main            , 6
Up Type= 0
Dn Type= 1
Dn Known WS=2972.28
DSS Import GetInterval= 0
DSS Import GetPeak= 0
DSS Import FillOption= 0

--- VANCERN_T1.g01 (geometry) ---

Geom Title=Geometry
Program Version=5.07

River Reach=VANCERN_T1      ,Main
Reach XY= 30
2365957.68330395581348.9268383232365970.57632288581341.387483314
2366033.25270668581322.197889149 2366042.6454044581317.224801973
2366062.11518177581302.5004220012366083.35759333581290.430892318
 2366107.0409449581281.6900961552366124.54976818581281.556894332
2366150.95457095 581291.07459183 2366160.0841459581292.233710259
2366209.88227466 581290.280958222366267.71385196581283.251116663
2366315.11992508581285.7593137622366325.37056077581284.109382644
2366347.72287825  581277.13793992366384.41276553581269.804293171
2366418.62103048581256.2350945622366456.51662385581253.536937237
2366500.21666771 581240.063210892366513.30752081 581241.60257791
 2366547.7792367581262.2823265942366601.30931333581281.094624922
2366630.55400547581294.1520134812366657.82593256581303.065381497
2366692.90164983581308.0145185892366723.28347883581315.290422678
2366748.95403117 581317.177557992366790.55663827581326.041057318
2366798.53037557581325.2379093322366811.59300002581317.714000002

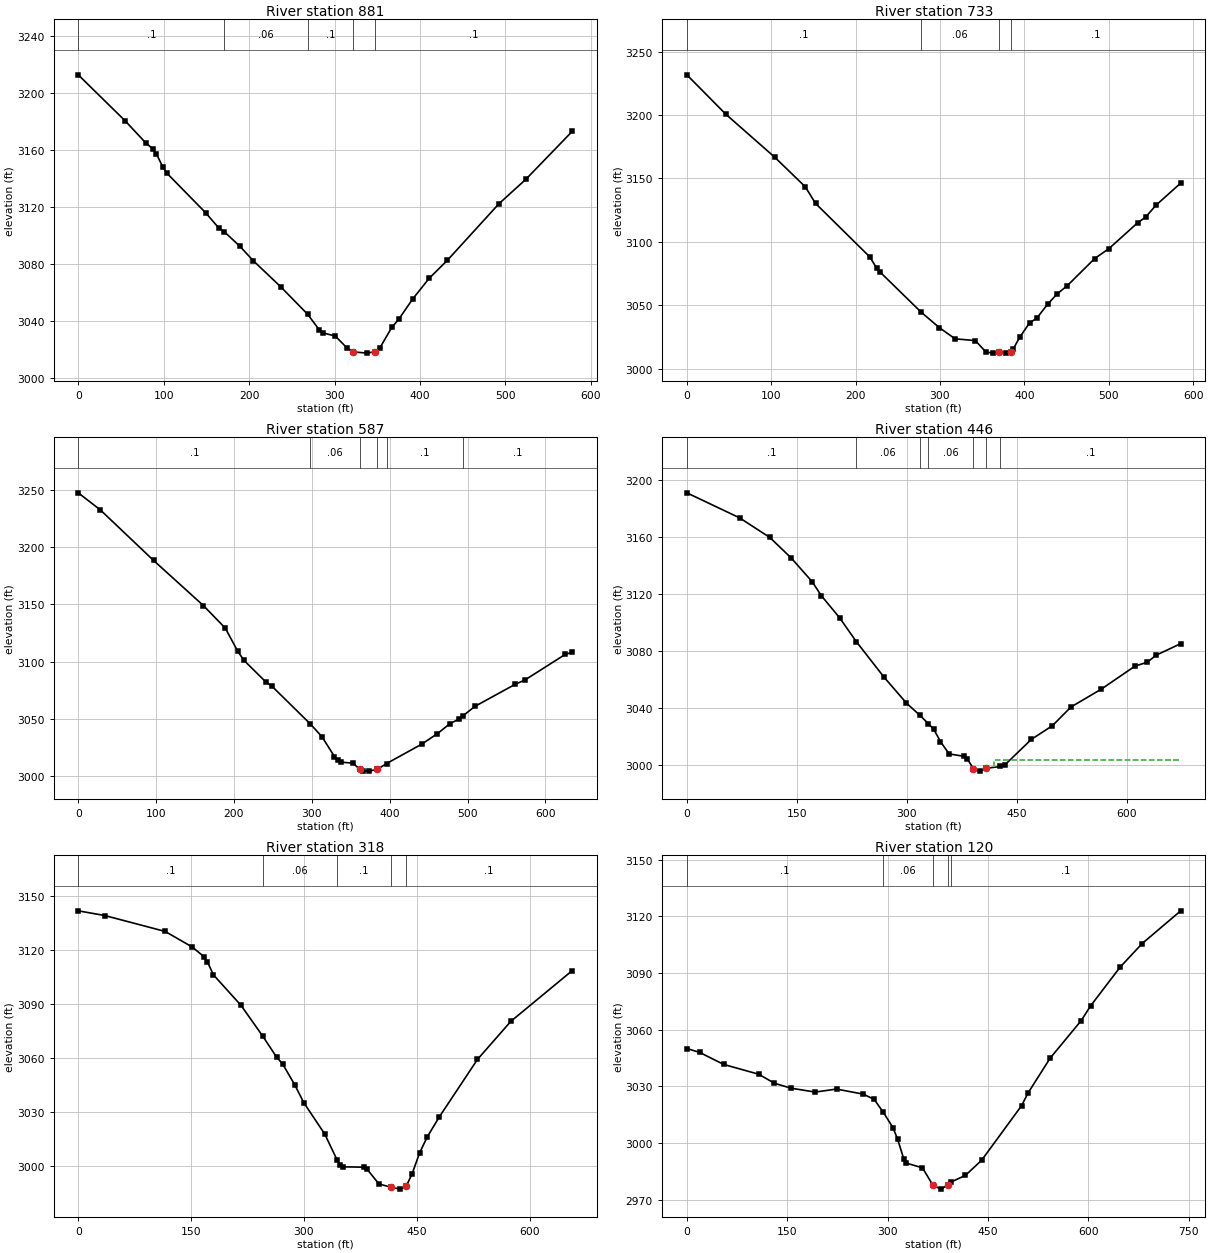
Type RM Length L Ch R = 1 ,881     ,147.3,147.3,147.3
XS GIS Cut Line= 2
2366025.93899787581669.1828899042365932.70079561581098.620756672
#Sta/Elev= 30
       0 3213.07      55 3180.73    79.3 3165.11    87.4 3161.07    91.5 3157.63
    98.8 3148.55   103.6 3144.11   149.1 3116.26   164.4 3105.62  171.083102.817
   188.8 3092.94     205 3082.49   237.4 3064.02  268.61 3044.91     282 3034.12
     286 3031.95   300.9 3029.66   314.8 3021.18   321.8 3018.56     338 3017.66
   347.7  3018.7   353.2 3021.43     367 3035.67   375.2 3041.42   391.3 3055.49
   410.7 3070.11   431.9  3082.7   492.7 3122.68   523.9 3139.65578.1302 3173.28
#Mann= 5 ,-1 , 0
       0      .1       0  171.08     .06       0  268.61      .1       0
   321.8    .045       0   347.7      .1       0
Bank Sta=321.8,347.7
XS Rating Curve= 0 ,0
Exp/Cntr(USF)=0,0
Exp/Cntr=0.3,0.1

Type RM Length L Ch R = 1 ,733     ,146.6,146.6,146.6
XS GIS Cut Line= 2
2366155.35918906581658.0499702322366078.82036631581077.746532286
#Sta/Elev= 30
       0 3231.69    46.1 3200.68   104.1 3166.75   140.4 3143.39   152.5 3130.31
     217    3088   225.1 3079.08   229.1 3076.12  277.553044.628   299.2 3032.38
   317.9 3023.55     342 3022.13   354.2 3013.26   362.3 3012.27   370.5 3013.03
   378.4 3012.26   384.1 3013.54   386.5 3015.16   394.5 3024.76   406.2 3036.15
   414.7 3039.76   427.5 3050.78   438.9 3058.95     451 3065.52   483.3 3086.81
   500.3  3094.7   534.5 3115.13   543.8 3119.54   555.9  3128.8585.3292 3146.36
#Mann= 4 ,-1 , 0
       0      .1       0  277.55     .06       0   370.5    .045       0
   384.1      .1       0
Bank Sta=370.5,384.1
XS Rating Curve= 0 ,0
Exp/Cntr(USF)=0,0
Exp/Cntr=0.3,0.1

Type RM Length L Ch R = 1 ,587     ,140.9,140.9,140.9
XS GIS Cut Line= 2
2366272.25484563581659.4415851912366234.68124173581026.256778799
#Sta/Elev= 30
       0 3247.63    28.4  3232.7    96.7 3188.51   160.8 3148.98   188.9 3129.25
   204.9 3108.96   212.9 3101.05     241 3082.15     249 3078.32  298.163045.415
   313.1 3034.21   329.1 3016.91   333.1 3013.57   337.1 3012.05   353.2 3011.13
   361.3 3005.75   365.2  3004.5   373.2 3004.18     384 3005.68  396.123010.848
   441.3 3027.82   461.4 3037.01   477.4  3045.7   489.4 3049.87  494.093052.512
   509.4  3060.8   561.5 3080.24   573.6 3083.85   625.6 3106.34634.2986 3108.13
#Mann= 6 ,-1 , 0
       0      .1       0  298.16     .06       0   361.3    .045       0
     384     .06       0  396.12      .1       0  494.09      .1       0
Bank Sta=361.3,384
XS Rating Curve= 0 ,0
Exp/Cntr(USF)=0,0
Exp/Cntr=0.3,0.1

Type RM Length L Ch R = 1 ,446     ,128.1,128.1,128.1
XS GIS Cut Line= 3
2366379.40919748581656.6583552732366435.07379584581435.391576775
2366315.39490936581006.774169372
#Sta/Elev= 30
       0 3190.72    71.9 3173.15     113 3159.42   142.1 3145.06   170.9 3128.28
   183.3 3118.51   208.1 3103.08  231.093086.201   268.7 3061.35   299.3 3043.13
  317.543034.579   329.3 3028.64   336.7 3024.63   345.7 3016.09   357.4 3007.47
   378.2 3005.72   382.3 3003.91   390.6 2997.11     399 2995.36   407.9 2997.36
  427.512998.611   433.4 2999.69   469.6 3017.65   498.3 3027.27   523.5 3040.34
   565.1 3052.97   610.8 3069.07   627.4 3071.77   639.8 3076.77673.1735 3084.85
#Mann= 7 ,-1 , 0
       0      .1       0  231.09     .06       0  317.54      .1       0
   329.3     .06       0   390.6    .045       0   407.9     .06       0
  427.51      .1       0
#XS Ineff= 2 , 0
                          418.88         3003.19
Permanent Ineff=
       F       F
Bank Sta=390.6,407.9
XS Rating Curve= 0 ,0
Exp/Cntr(USF)=0,0
Exp/Cntr=0.3,0.1

Type RM Length L Ch R = 1 ,318     ,197.3,197.3,197.3
XS GIS Cut Line= 3
2366494.91323908581666.3996599862366515.78746347581136.194360568
2366447.59833047581030.431623676
#Sta/Elev= 30
       0 3141.73    35.5  3139.1   115.6 3130.28   151.6 3121.64   167.6 3116.13
   171.6 3113.54   179.6 3106.26   216.4 3089.27  244.943072.396   263.7 3060.55
   271.7 3056.76   287.7 3045.28   299.7 3035.38   327.8 3017.79  344.323003.321
   347.8 3000.92   351.8 2999.72   379.8  2999.5   383.8 2998.44   399.8 2990.17
   415.3 2988.47   427.8 2987.34   435.8 2988.82   443.9 2995.96   453.8  3007.5
   463.9 3016.29   479.9 3027.37   530.6 3059.26     575 3080.41656.4553  3108.5
#Mann= 5 ,-1 , 0
       0      .1       0  244.94     .06       0  344.32      .1       0
   415.3    .045       0   435.8      .1       0
Bank Sta=415.3,435.8
XS Rating Curve= 0 ,0
Exp/Cntr(USF)=0,0
Exp/Cntr=0.3,0.1

Type RM Length L Ch R = 1 ,120     ,120.4,120.4,120.4
XS GIS Cut Line= 3
2366663.29864914581685.8822694142366700.87225303581240.565482501
2366500.47969892581029.040008717
#Sta/Elev= 30
       0  3050.1    19.1 3048.03    55.2 3041.65   107.4  3036.5     131 3031.69
   155.5 3029.13   191.7 3027.05   223.8 3028.64   263.9 3025.94     280 3023.18
  293.793016.308   308.1 3008.24   315.2 3001.97   324.1 2991.88     328 2989.47
   352.2 2986.98   367.8 2977.79   379.8 2975.71   389.7  2977.8  394.162979.336
   416.5    2983   440.6 2990.96   500.5 3019.92   509.8 3026.43     543 3044.96
   589.6  3064.9   603.5 3072.63   647.7 3093.14   680.6 3105.62738.2755 3122.93
#Mann= 5 ,-1 , 0
       0      .1       0  293.79     .06       0   367.8    .045       0
   389.7     .06       0  394.16      .1       0
Bank Sta=367.8,389.7
XS Rating Curve= 0 ,0
Exp/Cntr(USF)=0,0
Exp/Cntr=0.3,0.1

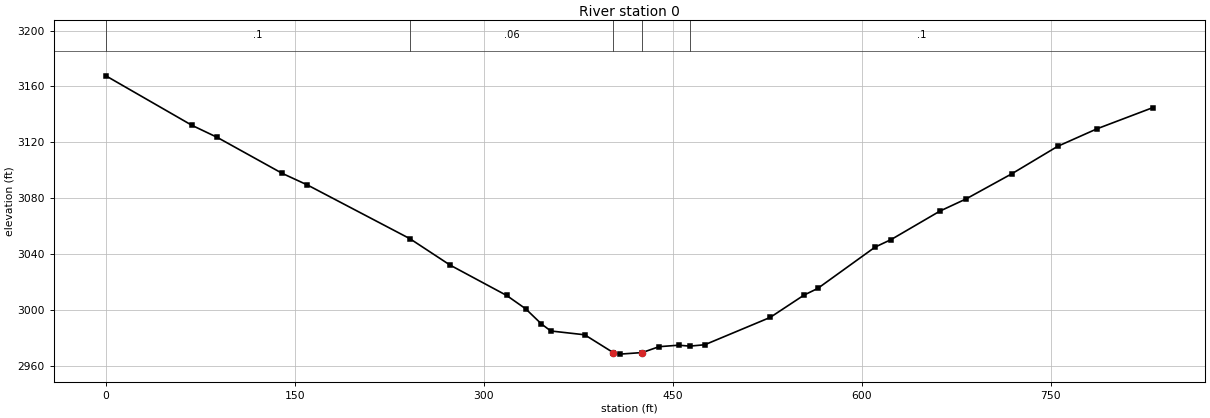
Type RM Length L Ch R = 1 ,0       ,,,
XS GIS Cut Line= 3
2367059.87737855581649.6908245952366813.24559435581319.714999329
2366546.33959435580996.538999329
#Sta/Elev= 30
       0 3167.57    68.4 3132.09    88.4  3123.5     140 3097.72     160 3089.41
  241.233051.005   273.2 3032.07   318.1 3010.33   333.1 3000.84   345.7 2989.92
   353.1 2984.92     380  2982.2   402.8 2969.36     408 2968.35   425.7 2969.48
     439 2973.67   454.5 2974.74   463.42974.081   475.3 2975.06   527.2 2994.62
   554.1 3010.62   564.9 3015.34   610.6 3045.03   623.2 3050.35     662 3070.77
   682.8  3079.5   719.1  3097.5   755.4 3117.11   786.8 3129.72831.1041 3144.87
#Mann= 5 ,-1 , 0
       0      .1       0  241.23     .06       0   402.8    .045       0
   425.7     .06       0   463.4      .1       0
Bank Sta=402.8,425.7
XS Rating Curve= 0 ,0
Exp/Cntr(USF)=0,0
Exp/Cntr=0.3,0.1
LCMann Table=0

Chan Stop Cuts=-1
Use User Specified Reach Order=0
Composite Channel Slope=5